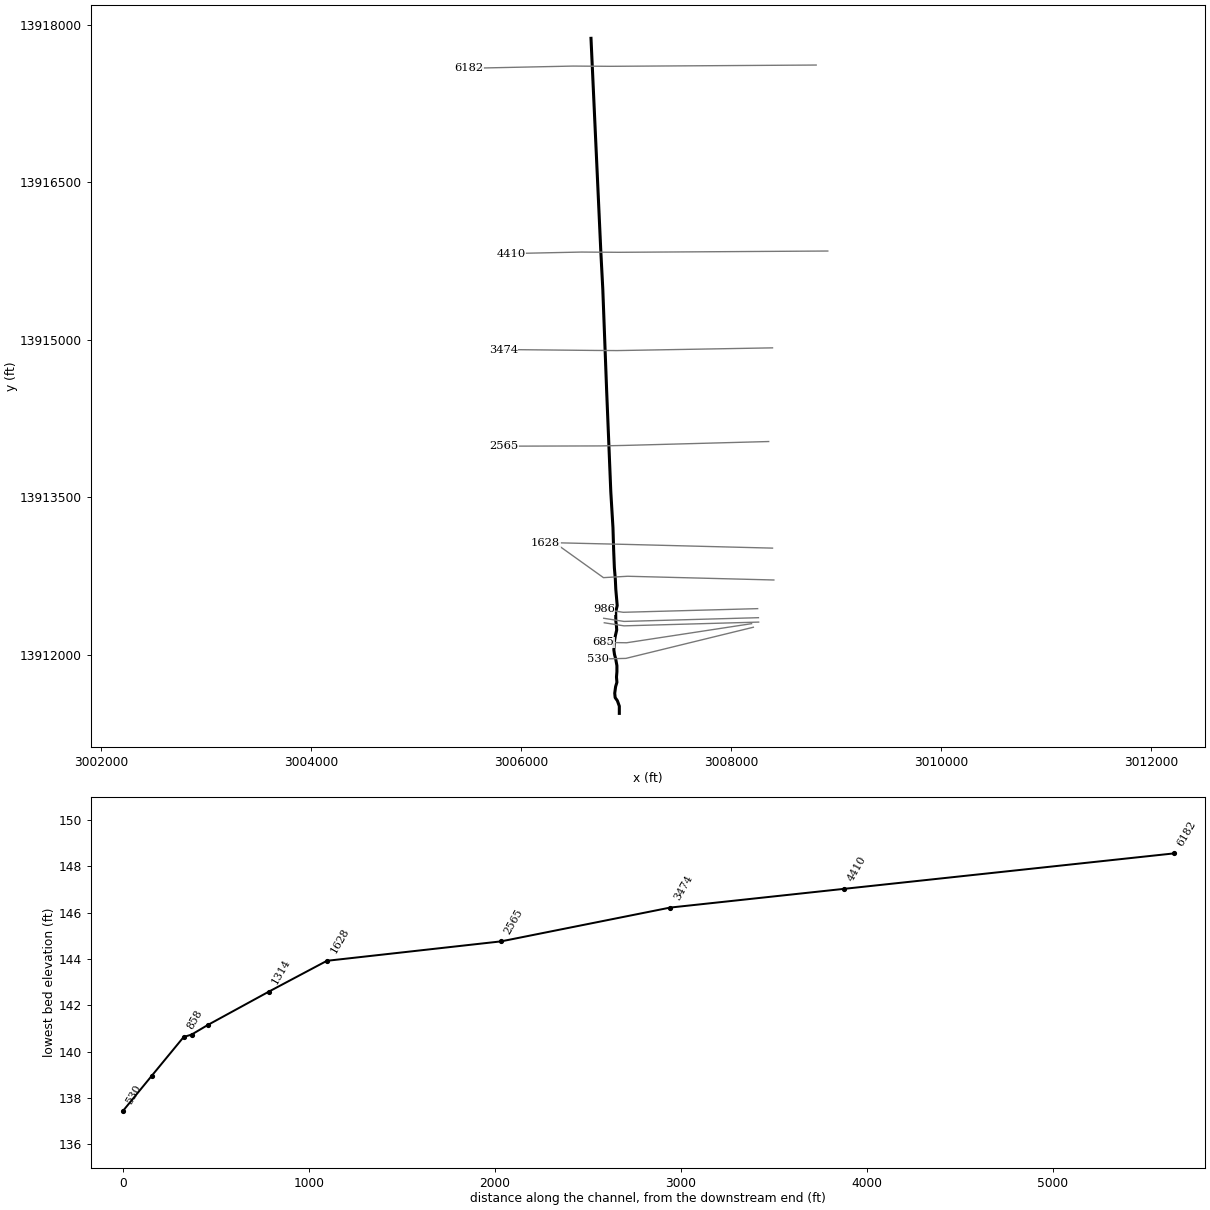
--- K152-00-00.prj (project) ---

Proj Title=K152-00-00
Current Plan=p06
Default Exp/Contr=0.3,0.1
English Units
Geom File=g01
Flow File=f07
Flow File=f06
Plan File=p01
Plan File=p06
Y Axis Title=Elevation
X Axis Title(PF)=Main Channel Distance
X Axis Title(XS)=Station
BEGIN DESCRIPTION:
Cypress Creek Watershed
Trib 37.1
HCFCD Unit K152-00-00
Flood Hazard Model
10, 2, 1, 0.2%
Filename K152-00-00
Prepared by:  Halff Associates, Inc.  DATE:  03-26-04
Reviewed by:  _____________________  DATE:  __________________
STATUS (Final)
TROPICAL STORM ALLISON RECOVERY PROJECT
END DESCRIPTION:
DSS File=dss
DSS Export Rating Curves= 0
DSS Export Rating Curve Sorted= 0
DSS Export Volume Flow Curves= 0
DXF OffsetX= 0
DXF OffsetY= 0
DXF ScaleX= 1
DXF ScaleY= 10

--- K152-00-00.p06 (plan) ---

Plan Title=Effective FW 2013
Program Version=3.13
Short Identifier=Eff FW 2013
Geom File=g01
Flow File=f06
Subcritical Flow
K Sum by GR= 0
Std Step Tol= 0.01
Critical Tol= 0.01
Num of Std Step Trials= 20
Max Error Tol= 0.3
Flow Tol Ratio= 0.001
Split Flow NTrial= 30
Split Flow Tol= 0.02
Split Flow Ratio= 0.02
Log Output Level= 0
Friction Slope Method= 1
Unsteady Friction Slope Method= 2
Unsteady Bridges Friction Slope Method= 1
Parabolic Critical Depth
Global Vel Dist= 0 , 0 , 0
Global Log Level= 0
CheckData=True
Encroach Param=-1 ,0,0, 2
Encroach River=K152-00-00
Encroach Reach=K152-00-00_0005
Encroach Node=6182
       1  4984.4  5026.2
Encroach Node=4410
       1  4973.8  5043.6
Encroach Node=3474
       1    4973  5038.7
Encroach Node=2565
       1  4967.2  5026.8
Encroach Node=1628
       1  4957.5  5034.4
Encroach Node=1314
       1  4960.8  5034.4
Encroach Node=986
       1  4980.1 5011.27
Encroach Node=900
       1  4958.6  5010.8
Encroach Node=858
       1  4978.6  5010.8
Encroach Node=685
       1  4978.6  5007.2
Encroach Node=530
       1  4978.6  5010.8
BEGIN DESCRIPTION:
FEMA Effective Floodway October 2013
END DESCRIPTION:
Computation Interval=1HOUR
Output Interval=1HOUR
Run HTab= 0
Run UNet= 0
Run PostProcess= 0
UNET Theta= 1
UNET Theta Warmup= 1
UNET ZTol= 0.02
UNET ZSATol= 0.1
UNET MxIter= 20
UNET MaxInSteps= 20
UNET DtIC= 0
UNET DtMin= 0
UNET MaxCRTS= 20
UNET WFStab= 2
UNET SFStab= 1
UNET WFX= 1
UNET SFX= 1
UNET DSS MLevel= 4
UNET DZMax Abort= 100
UNET Convert EG Bridges=-1
UNET Use Existing IB Tables=-1
UNET Froude Reduction=False
UNET Froude Limit= 1
UNET Froude Power= 10
Instantaneous Interval=1HOUR
Write IC File= 0
Echo Input=False
Echo Output=False
Write Detailed= 0
Detailed Automatic Start=False, 10

--- K152-00-00.p01 (plan) ---

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Plan Title=Effective MP 2013
Short Identifier=Eff MP 2013
Geom File=g01
Flow File=f07
FEMA Effective MP October 2013

--- K152-00-00.f06 (steady flow) ---

Flow Title=Effective FW 2013
Program Version=3.13
Number of Profiles= 2
Profile Names=1PCT_100yr,1PCTFloodway_10
River Rch & RM=K152-00-00,K152-00-00_0005       ,6182
      15      15
River Rch & RM=K152-00-00,K152-00-00_0005       ,3474
     141     141
River Rch & RM=K152-00-00,K152-00-00_0005       ,2565
     153     153
River Rch & RM=K152-00-00,K152-00-00_0005       ,1628
     195     195
River Rch & RM=K152-00-00,K152-00-00_0005       ,685
     202     202
Boundary for River Rch & Prof#=K152-00-00,K152-00-00_0005       , 1
Up Type= 0
Dn Type= 3
Dn Slope=0.0014
Boundary for River Rch & Prof#=K152-00-00,K152-00-00_0005       , 2
Up Type= 0
Dn Type= 3
Dn Slope=0.0014
DSS Import GetInterval= 0
DSS Import GetPeak= 0
DSS Import FillOption= 0

--- K152-00-00.f07 (steady flow) ---

Flow Title=Effective MP 2013
Program Version=3.13
Number of Profiles= 4
Profile Names=10PCT_10yr,2PCT_50yr,1PCT_100yr,0.2PCT_500yr
River Rch & RM=K152-00-00,K152-00-00_0005       ,6182
       6      11      15      26
River Rch & RM=K152-00-00,K152-00-00_0005       ,3474
      55     108     141     248
River Rch & RM=K152-00-00,K152-00-00_0005       ,2565
      60     117     153     269
River Rch & RM=K152-00-00,K152-00-00_0005       ,1628
      76     150     195     343
River Rch & RM=K152-00-00,K152-00-00_0005       ,685
      79     155     202     356
Boundary for River Rch & Prof#=K152-00-00,K152-00-00_0005       , 1
Up Type= 0
Dn Type= 3
Dn Slope=0.0014
Boundary for River Rch & Prof#=K152-00-00,K152-00-00_0005       , 2
Up Type= 0
Dn Type= 3
Dn Slope=0.0014
Boundary for River Rch & Prof#=K152-00-00,K152-00-00_0005       , 3
Up Type= 0
Dn Type= 3
Dn Slope=0.0014
Boundary for River Rch & Prof#=K152-00-00,K152-00-00_0005       , 4
Up Type= 0
Dn Type= 3
Dn Slope=0.0014
DSS Import GetInterval= 0
DSS Import GetPeak= 0
DSS Import FillOption= 0

--- K152-00-00.g01 (geometry) ---

Geom Title=K152-00-00 2013
Program Version=3.13

River Reach=K152-00-00      ,K152-00-00_0005
Reach XY= 30
      3006664.68      13917869.1      3006758.63     13915831.47
        3006777.       13915483.       3006813.5       13914520.
      3006853.25       13913552.      3006873.87     13913209.55
      3006880.61     13912991.62      3006887.35      13912827.6
      3006896.33     13912719.76      3006900.83     13912623.15
      3006914.31     13912468.13      3006899.89     13912406.06
      3006901.36     13912319.05      3006907.34     13912270.99
      3006909.43     13912235.57      3006896.93      13912181.4
      3006886.51     13912117.86      3006882.34     13912045.99
      3006888.59     13912002.24      3006899.01     13911964.74
      3006911.51     13911895.99      3006911.51     13911837.65
      3006907.34     13911787.65      3006911.51     13911737.65
      3006899.01     13911695.99      3006890.68     13911633.49
      3006894.84     13911591.82      3006915.68     13911562.65
      3006934.43     13911510.57      3006934.43      13911441.8

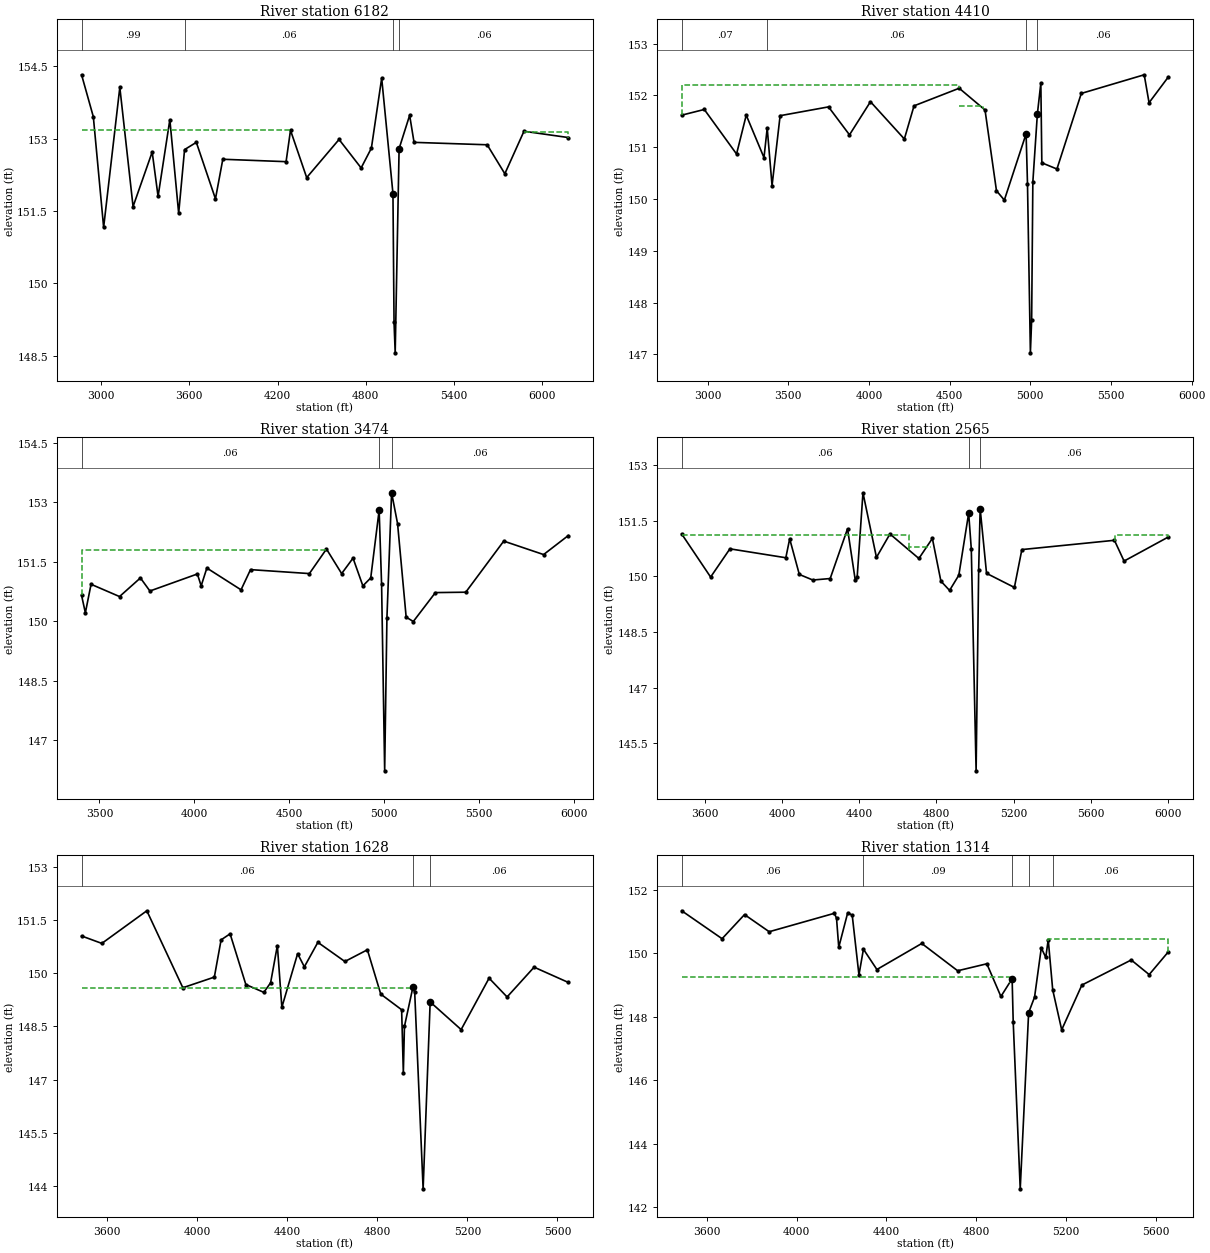
Type RM Length L Ch R = 1 ,6182    ,1773.8,1772,1771
BEGIN DESCRIPTION:
Cross Section K152-00-00-X7-Interp
END DESCRIPTION:
XS GIS Cut Line= 4
       3008808.8      13917614.8      3006849.13     13917602.68
      3006492.18     13917605.01       3005501.2     13917584.02
#Sta/Elev= 30
  2868.1  154.32  2948.1  153.45  3018.1  151.16  3128.1  154.06  3218.1  151.59
  3348.1  152.72  3388.1   151.8  3468.1  153.39  3528.1  151.45  3568.1  152.77
  3648.1  152.92  3778.1  151.75  3828.1  152.57  4258.1  152.52  4288.1  153.17
  4398.1  152.19  4618.1  152.98  4768.1  152.39  4837.8   152.8  4907.8  154.25
  4984.4  151.86  4991.8  149.19  4999.6  148.56  5026.2  152.79  5097.8  153.48
  5127.8  152.92  5624.8  152.87  5744.8  152.27  5874.8  153.15    6176  153.02
#Mann= 4 ,-1 , 0
  2868.1     .99       0  3568.1     .06       0  4984.4     .07       0
  5026.2     .06       0
#XS Ineff= 4 ,-1
  2868.1 4288.07  153.17 5874.03    6176  153.14 4288.07    4900   152.8
    5100 5874.03   152.8
Permanent Ineff=
       F       F       F       F
Bank Sta=4984.4,5026.2
Exp/Cntr=0.3,0.1

Type RM Length L Ch R = 1 ,4410    ,937,936,935
BEGIN DESCRIPTION:
Cross Section K152-00-00-X6 **SEE NOTE**
This cross section cannot be extended.  This is overflow to K100-00-00
END DESCRIPTION:
XS GIS Cut Line= 4
       3008919.3       13915844.      3006929.62     13915831.84
      3006572.67     13915834.17      3005902.81      13915819.9
#Sta/Elev= 30
  2839.2  151.62  2979.2  151.73  3179.2  150.87  3239.2  151.62  3349.2   150.8
  3369.2  151.37  3399.2  150.26  3449.2  151.61  3749.2  151.78  3879.2  151.24
  4009.2  151.88  4219.2  151.16  4279.2   151.8  4559.2  152.14  4719.2  151.72
  4790.2  150.16    4839  149.98  4973.8  151.26  4982.4   150.3  5000.4  147.03
  5008.2  147.66  5015.6  150.33  5043.6  151.64  5065.2  152.24  5071.3   150.7
  5164.9  150.58  5315.9  152.04  5705.9   152.4  5735.9  151.86  5855.9  152.36
#Mann= 4 ,-1 , 0
  2839.2     .07       0  3369.2     .06       0  4973.8     .07       0
  5043.6     .06       0
#XS Ineff= 3 ,-1
  2839.2    4560   152.2    5520  5855.9   152.2    4560 4709.55   151.8
Permanent Ineff=
       F       F       F
Bank Sta=4973.8,5043.6
Exp/Cntr=0.3,0.1

Type RM Length L Ch R = 1 ,3474    ,910,909,907.6
BEGIN DESCRIPTION:
Cross Section K152-00-00-X5 **SEE NOTE**
This cross section cannot be extended.  This is overflow to K159-00-00 and K100-00-00
END DESCRIPTION:
XS GIS Cut Line= 4
        3008393.       13914922.      3006913.62      13914896.1
      3006699.46     13914897.46      3005829.55      13914906.1
#Sta/Elev= 30
  3405.6  150.65  3425.6  150.21  3455.6  150.93  3605.6  150.62  3715.6  151.09
  3765.6  150.76  4015.6  151.19  4035.6  150.89  4065.6  151.34  4245.6  150.79
  4295.6   151.3  4605.6   151.2  4695.6  151.82  4775.6   151.2  4835.6  151.59
  4887.4  150.89  4928.8  151.09  4973.1   152.8    4986  150.93  5002.2  146.22
  5014.1  150.08  5038.7  153.24  5070.2  152.46  5115.4   150.1  5153.1  149.99
  5269.4  150.72  5429.4  150.73  5629.4  152.02  5839.4  151.68  5969.4  152.16
#Mann= 3 ,-1 , 0
  3405.6     .06       0  4973.1     .07       0  5038.7     .06       0
#XS Ineff= 2 , 0
       0    4695   151.8               0
Permanent Ineff=
       F       F
Bank Sta=4973.1,5038.7
Exp/Cntr=0.3,0.1

Type RM Length L Ch R = 1 ,2565    ,936,937,937.5
BEGIN DESCRIPTION:
Cross Section K152-00-00-X4 **SEE NOTE**
This cross section cannot be extended.  This is overflow to K159-00-00
END DESCRIPTION:
XS GIS Cut Line= 4
      3008356.52      13914030.1      3006987.63     13913993.11
      3006753.04     13913988.31      3005833.02       13913986.
#Sta/Elev= 30
    3479  151.14    3629  149.98    3729  150.74    4019   150.5    4039  151.01
    4089  150.05    4159   149.9    4249  149.94    4339  151.28    4379   149.9
    4389  149.98    4419  152.25    4489  150.51    4559  151.14    4709  150.48
    4779  151.02  4823.2  149.87  4868.2  149.62  4916.2  150.03  4967.2   151.7
  4980.8  150.74  5005.8  144.76  5019.1  150.18  5026.8  151.82  5059.9  150.08
  5204.3   149.7  5243.1  150.72  5723.1  150.97  5773.1  150.41  6003.1  151.06
#Mann= 3 ,-1 , 0
    3479     .06       0  4967.2     .07       0  5026.8     .06       0
#XS Ineff= 4 ,-1
    3479    4660   151.1    5725  6003.1   151.1    4660    4770   150.8
    5420    5725   150.8
Permanent Ineff=
       F       F       F       F
Bank Sta=4967.2,5026.8
Exp/Cntr=0.3,0.1

Type RM Length L Ch R = 1 ,1628    ,319.3,314,313
BEGIN DESCRIPTION:
Cross Section K152-00-00-X3
END DESCRIPTION:
XS GIS Cut Line= 4
        3008393.      13913015.2       3007000.8      13913050.7
      3006732.73     13913056.85      3006230.98     13913068.76
#Sta/Elev= 30
  3485.4  151.05  3575.4  150.84  3775.4  151.76  3935.4  149.59  4075.4  149.89
  4105.4  150.94  4145.4  151.11  4215.4  149.68  4295.4  149.46  4325.4  149.73
  4355.4  150.78  4375.4  149.04  4445.4  150.55  4475.4  150.18  4535.4  150.87
  4655.4  150.33  4755.4  150.66  4814.9  149.41  4907.6  148.97  4915.2  147.19
  4920.1   148.5  4957.5   149.6  4965.6  149.47  5003.1  143.92  5034.4  149.19
    5172  148.41  5296.2  149.86  5376.2  149.33  5496.2  150.17  5648.1  149.74
#Mann= 3 ,-1 , 0
  3485.4     .06       0  4957.5     .07       0  5034.4     .06       0
#XS Ineff= 2 , 0
       0 4956.45  149.59  5034.4       0  149.19
Permanent Ineff=
       F       F
Bank Sta=4957.5,5034.4
Exp/Cntr=0.3,0.1

Type RM Length L Ch R = 1 ,1314    ,329,328,327
BEGIN DESCRIPTION:
Cross Section K152-00-00-X2-interp
END DESCRIPTION:
XS GIS Cut Line= 4
       3008405.9      13912711.8      3007013.71     13912747.36
      3006783.22     13912734.18      3006339.44     13913051.78
#Sta/Elev= 30
  3488.1  151.34  3668.1  150.46  3768.1  151.22  3878.1  150.68  4168.1  151.26
  4178.1  151.11  4188.1  150.19  4228.1  151.28  4248.1   151.2  4278.1  149.32
  4298.1  150.13  4358.1  149.49  4558.1  150.31  4718.1  149.45  4848.1  149.67
  4910.8  148.64  4960.8   149.2  4965.6  147.85  4996.9  142.58  5034.4  148.13
  5060.8  148.62  5090.8  150.17  5110.8  149.87  5121.7  150.43  5141.7  148.85
  5181.7  147.59  5271.7     149  5491.7  149.79  5571.7  149.33  5657.4  150.05
#Mann= 5 ,-1 , 0
  3488.1     .06       0  4298.1     .09       0  4960.8     .07       0
  5034.4     .09       0  5141.7     .06       0
#XS Ineff= 2 , 0
       0  4950.1  149.24 5121.09       0  150.45
Permanent Ineff=
       F       F
Bank Sta=4960.8,5034.4
Exp/Cntr=0.3,0.1

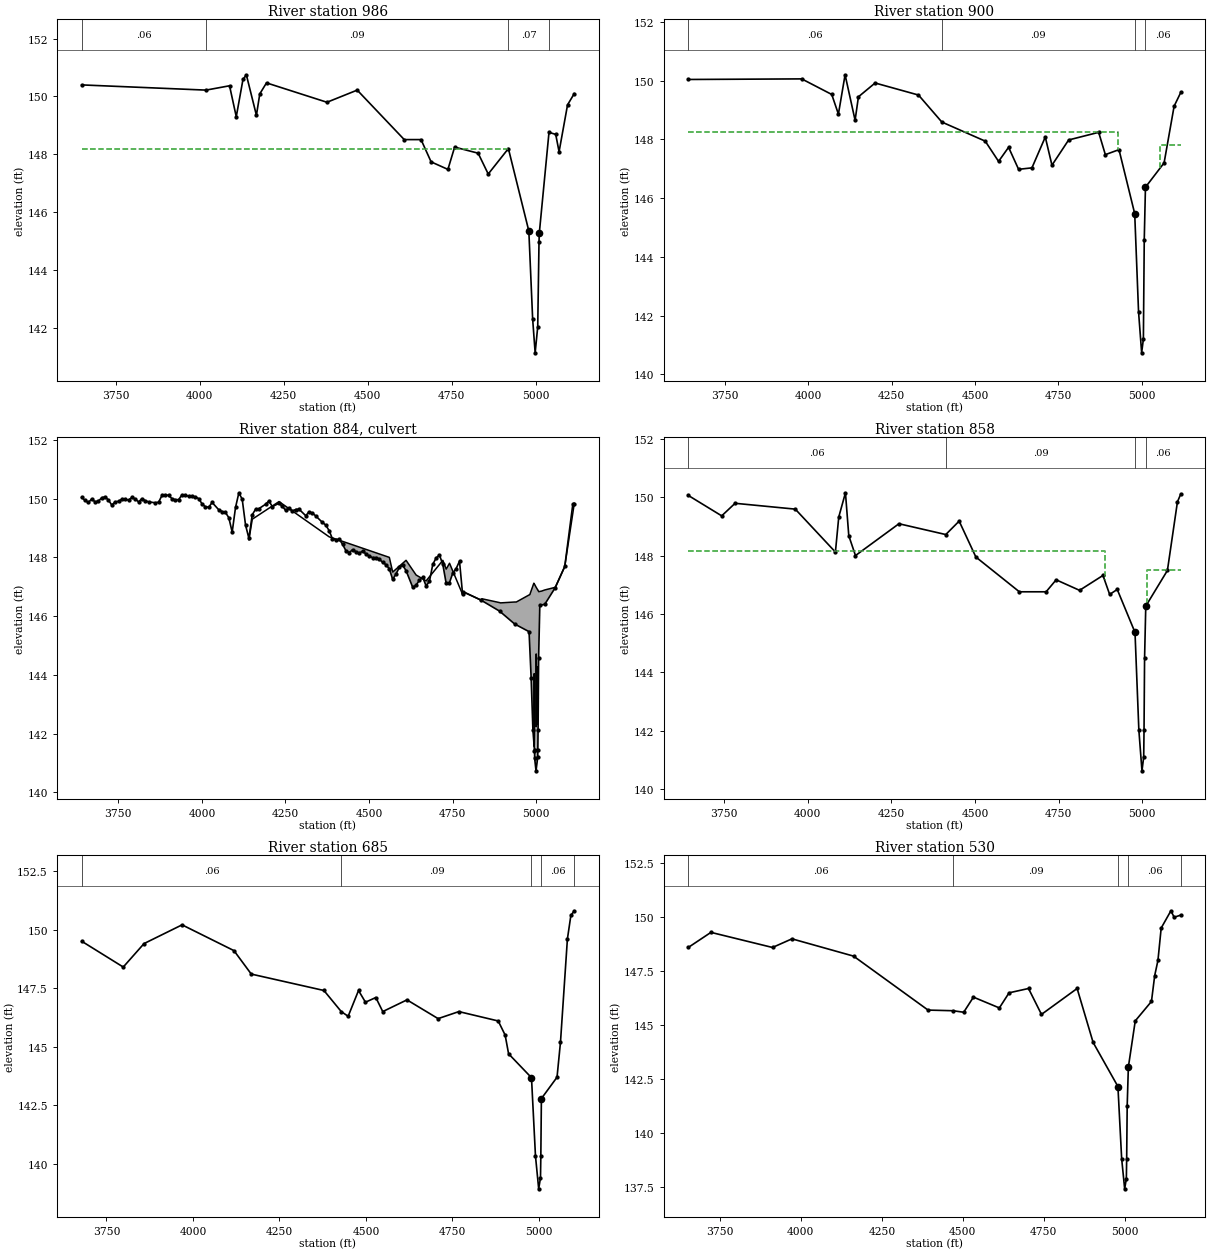
Type RM Length L Ch R = 1 ,986     ,85,86,120
BEGIN DESCRIPTION:
K152-00-00-S01_CULVERT - US - XS4
END DESCRIPTION:
XS GIS Cut Line= 4
       3008251.4       13912439.      3006971.05     13912404.19
      3006827.52     13912426.56      3006788.07      13912432.7
#Sta/Elev= 30
  3649.2   150.4  4019.2  150.22  4089.2  150.37  4109.2   149.3  4129.2  150.59
  4139.2  150.75  4169.2  149.35  4179.2  150.09  4199.2  150.47  4379.2   149.8
  4469.2  150.22  4609.2  148.51  4659.2  148.51  4689.2  147.74  4739.2  147.48
  4759.2  148.25  4829.2  148.04  4859.2  147.32  4919.2   148.2  4980.1  145.35
 4991.39  142.32 4998.88  141.14 5006.55  142.04 5010.38  144.98 5011.27  145.28
  5040.1  148.76  5060.1  148.69  5070.1  148.09  5095.3  149.71  5115.3   150.1
#Mann= 4 ,-1 , 0
  3649.2     .06       0  4019.2     .09       0  4919.2     .07       0
  5040.1     .06       0
#XS Ineff= 2 , 0
       0 4917.83  148.19               0
Permanent Ineff=
       F       F
Bank Sta=4980.1,5011.27
Exp/Cntr=0.5,0.3

Type RM Length L Ch R = 1 ,900     ,45,42,31
BEGIN DESCRIPTION:
K152-00-00-S01_CULVERT - US - XS3
END DESCRIPTION:
XS GIS Cut Line= 4
        3008259.      13912352.9      3006978.78     13912317.25
      3006835.25     13912339.62       3006785.9      13912347.3
#Sta/Elev= 30
  3640.6  150.04  3980.6  150.06  4070.6  149.53  4090.6  148.86  4110.6   150.2
  4140.6  148.65  4150.6  149.45  4200.6  149.92  4330.6  149.51  4400.6  148.59
  4530.6  147.94  4570.6  147.25  4600.6  147.73  4630.6  146.98  4670.6  147.03
  4710.6  148.08  4730.6  147.12  4780.6  147.98  4870.6  148.24  4890.6  147.48
  4931.5  147.65  4978.6  145.47  4990.1  142.13  4999.4  140.73  5004.6   141.2
  5007.2  144.58  5010.8  146.37  5066.7   147.2  5096.7  149.13  5116.7   149.6
#Mann= 4 ,-1 , 0
  3640.6     .06       0  4400.6     .09       0  4978.6     .07       0
  5010.8     .06       0
#XS Ineff= 2 , 0
       0    4930  148.24 5054.49       0   147.8
Permanent Ineff=
       F       F
Bank Sta=4978.6,5010.8
Exp/Cntr=0.5,0.3

Type RM Length L Ch R = 2 ,884     ,,,
BEGIN DESCRIPTION:
CULVERT
Structure ID: K152-00-00-S01
END DESCRIPTION:
Bridge Culvert--1,0,-1,-1, 0
Deck Dist Width WeirC Skew NumUp NumDn MinLoCord MaxHiCord MaxSubmerge Is_Ogee
19.5,10,2.6,0, 41, 41, , , 0.95, 0, 1,1,,
  4140.7  4150.7  4230.7  4380.7  4404.2  4560.7  4570.7  4610.7  4640.7  4670.7
  4720.7  4730.7  4740.7  4779.8  4781.2  4833.9  4837.8  4890.3    4893  4935.6
  4940.4  4978.6  4980.8  4984.8  4990.1  4992.9  4994.8  4995.2  4999.4  5004.6
  5004.9  5005.6  5007.2  5007.8  5010.8  5015.6  5025.5    5057  5062.2  5085.4
  5113.8
   148.6   149.3   149.9   148.7  148.61     148   147.5   147.9   147.4   147.2
   147.9   147.6   147.8  146.74  146.83  146.55  146.59  146.46  146.45  146.48
  146.48  146.72  146.73  146.86  147.03  147.12  147.08  147.08  146.99  146.89
  146.89  146.87  146.84  146.83  146.84  146.85  146.89  146.98  147.11  147.69
  149.83
                                                                                
                                                                                
                                                                                
                                                                                
        
  4140.7  4150.7  4230.7  4380.7  4404.2  4560.7  4570.7  4610.7  4640.7  4670.7
  4720.7  4730.7  4740.7  4779.8  4781.2  4833.9  4837.8  4890.3    4893  4935.6
  4940.4  4978.6  4980.8  4984.8  4990.1  4992.9  4994.8  4995.2  4999.4  5004.6
  5004.9  5005.6  5007.2  5007.8  5010.8  5015.6  5025.5    5057  5062.2  5085.4
  5113.8
   148.6   149.3   149.9   148.7  148.61     148   147.5   147.9   147.4   147.2
   147.9   147.6   147.8  146.74  146.83  146.55  146.59  146.46  146.45  146.48
  146.48  146.72  146.73  146.86  147.03  147.12  147.08  147.08  146.99  146.89
  146.89  146.87  146.84  146.83  146.84  146.85  146.89  146.98  147.11  147.69
  149.83
                                                                                
                                                                                
                                                                                
                                                                                
        
BR Coef= 1 , 1 , 0 ,1.25, 0 ,,,0.8,0,2,0,
WSPro=,,,, 1 ,,,, 0 ,,,, 0 ,,,,-1 ,-1 ,-1 , 0 , 0 , 0 , 0 , 0
Culvert=1,2.5,,34,0.024,0.5,1,2,3,141.55,4994,141.27,4994,Culvert #1  , 0 ,4
Culvert Bottom n=0.024
Culvert=1,2.5,,34,0.024,0.5,1,2,3,142.22,5000,141.63,5000,Culvert #2  , 0 ,4
Culvert Bottom n=0.024
Culvert=1,2,,34,0.024,0.5,1,2,3,142.29,5003.5,141.55,5003.5,Culvert #3  , 0 ,4
Culvert Bottom n=0.024
BR U #Sta/Elev= 129
  3640.6  150.04  3650.6  149.94  3660.6  149.87  3670.6  149.99  3680.6  149.89
  3690.6  149.92  3700.6  150.03  3710.6  150.06  3720.6  149.95  3730.6  149.78
  3740.6  149.89  3750.6  149.91  3760.6  149.98  3770.6  149.98  3780.6  149.95
  3790.6  150.04  3800.6  149.99  3810.6  149.89  3820.6     150  3830.6  149.93
  3840.6  149.89  3860.6  149.86  3870.6  149.88  3880.6  150.11  3890.6  150.13
  3900.6  150.11  3910.6     150  3920.6  149.96  3930.6  149.97  3940.6  150.13
  3950.6  150.12  3960.6  150.08  3970.6  150.08  3980.6  150.06  3990.6     150
  4000.6  149.82  4010.6  149.72  4020.6  149.71  4030.6  149.87  4050.6  149.62
  4060.6  149.56  4070.6  149.53  4080.6  149.35  4090.6  148.86  4100.6   149.7
  4110.6   150.2  4120.6  149.98  4130.6   149.1  4140.6  148.65  4150.6  149.45
  4160.6  149.64  4170.6  149.66  4190.6  149.81  4200.6  149.92  4210.6  149.73
  4230.6  149.84  4240.6  149.74  4250.6   149.6  4260.6  149.68  4270.6  149.58
  4280.6  149.63  4290.6  149.64  4310.6  149.42  4320.6  149.55  4330.6  149.51
  4340.6  149.41  4360.6  149.19  4370.6   149.1  4380.6  148.91  4390.6  148.63
  4400.6  148.59  4410.6  148.62  4420.6  148.45  4430.6  148.23  4440.6  148.16
  4450.6  148.26  4460.6  148.19  4470.6  148.14  4480.6  148.21  4490.6  148.12
  4500.6  148.04  4510.6  147.99  4520.6  147.99  4530.6  147.94  4540.6  147.83
  4550.6  147.75  4560.6  147.61  4570.6  147.25  4580.6  147.43  4590.6  147.66
  4600.6  147.73  4610.6  147.55  4630.6  146.98  4640.6  147.05  4650.6  147.22
  4660.6  147.32  4670.6  147.03  4680.6  147.18  4690.6  147.76  4700.6  147.98
  4710.6  148.08  4720.6  147.76  4730.6  147.12  4740.6  147.14  4750.6  147.47
  4760.6  147.62  4770.6  147.87  4779.8  146.74  4781.2  146.83  4833.9  146.55
  4890.3  146.17  4935.6  145.73  4978.6  145.47  4984.8   143.9  4990.1  142.13
  4994.8  141.42  4995.2  141.44  4995.2  141.17  4999.4  140.73  5004.6   141.2
  5004.9  141.44  5005.6  142.13  5007.2  144.58  5010.8  146.37  5025.5   146.4
    5057  146.97  5085.4  147.69  5109.6  149.82  5113.8  149.83
BR U #Mann= 4
  3640.6     .06  4400.6     .09  4978.6     .07  5010.8     .06
BR U Banks=4978.6,5010.8
BR D #Sta/Elev= 129
  3640.6  150.04  3650.6  149.94  3660.6  149.87  3670.6  149.99  3680.6  149.89
  3690.6  149.92  3700.6  150.03  3710.6  150.06  3720.6  149.95  3730.6  149.78
  3740.6  149.89  3750.6  149.91  3760.6  149.98  3770.6  149.98  3780.6  149.95
  3790.6  150.04  3800.6  149.99  3810.6  149.89  3820.6     150  3830.6  149.93
  3840.6  149.89  3860.6  149.86  3870.6  149.88  3880.6  150.11  3890.6  150.13
  3900.6  150.11  3910.6     150  3920.6  149.96  3930.6  149.97  3940.6  150.13
  3950.6  150.12  3960.6  150.08  3970.6  150.08  3980.6  150.06  3990.6     150
  4000.6  149.82  4010.6  149.72  4020.6  149.71  4030.6  149.87  4050.6  149.62
  4060.6  149.56  4070.6  149.53  4080.6  149.35  4090.6  148.86  4100.6   149.7
  4110.6   150.2  4120.6  149.98  4130.6   149.1  4140.6  148.65  4150.6  149.45
  4160.6  149.64  4170.6  149.66  4190.6  149.81  4200.6  149.92  4210.6  149.73
  4230.6  149.84  4240.6  149.74  4250.6   149.6  4260.6  149.68  4270.6  149.58
  4280.6  149.63  4290.6  149.64  4310.6  149.42  4320.6  149.55  4330.6  149.51
  4340.6  149.41  4360.6  149.19  4370.6   149.1  4380.6  148.91  4390.6  148.63
  4400.6  148.59  4410.6  148.62  4420.6  148.45  4430.6  148.23  4440.6  148.16
  4450.6  148.26  4460.6  148.19  4470.6  148.14  4480.6  148.21  4490.6  148.12
  4500.6  148.04  4510.6  147.99  4520.6  147.99  4530.6  147.94  4540.6  147.83
  4550.6  147.75  4560.6  147.61  4570.6  147.25  4580.6  147.43  4590.6  147.66
  4600.6  147.73  4610.6  147.55  4630.6  146.98  4640.6  147.05  4650.6  147.22
  4660.6  147.32  4670.6  147.03  4680.6  147.18  4690.6  147.76  4700.6  147.98
  4710.6  148.08  4720.6  147.76  4730.6  147.12  4740.6  147.14  4750.6  147.47
  4760.6  147.62  4770.6  147.87  4779.8  146.74  4781.2  146.83  4833.9  146.55
  4890.3  146.17  4935.6  145.73  4978.6  145.47  4984.8   143.9  4990.1  142.13
  4994.8  141.42  4995.2  141.44  4995.2  141.17  4999.4  140.73  5004.6   141.2
  5004.9  141.44  5005.6  142.13  5007.2  144.58  5010.8  146.37  5025.5   146.4
    5057  146.97  5085.4  147.69  5109.6  149.82  5113.8  149.83
BR D #Mann= 4
  3640.6     .06  4400.6     .09  4978.6     .07  5010.8     .06
BR D Banks=4978.6,5010.8
BC Design=,, 0 ,, 0 ,,,,,,
BC HTab HWMax=150.2

Type RM Length L Ch R = 1 ,858     ,170,173,184
BEGIN DESCRIPTION:
K152-00-00-S01_CULVERT - DS - XS2
END DESCRIPTION:
XS GIS Cut Line= 3
       3008261.2      13912310.9      3006979.02     13912275.16
      3006791.34      13912304.4
#Sta/Elev= 30
  3642.8  150.06  3742.8  149.36  3782.8  149.79  3962.8  149.59  4082.8  148.12
  4092.8  149.32  4112.8  150.15  4122.8  148.68  4142.8     148  4272.8  149.09
  4412.8  148.72  4452.8  149.18  4502.8  147.95  4632.8  146.76  4712.8  146.76
  4742.8  147.17  4812.8  146.81  4882.8  147.32  4902.8  146.67  4925.5  146.84
  4978.6  145.37  4990.1  142.03  4999.4  140.63  5004.6   141.1  5005.6  142.03
  5007.2  144.48  5010.8  146.27  5075.5  147.49  5105.5  149.84  5115.5  150.11
#Mann= 4 ,-1 , 0
  3642.8     .06       0  4412.8     .09       0  4978.6     .07       0
  5010.8     .06       0
#XS Ineff= 2 , 0
       0    4888  148.15 5014.49       0   147.5
Permanent Ineff=
       F       F
Bank Sta=4978.6,5010.8
Exp/Cntr=0.5,0.3

Type RM Length L Ch R = 1 ,685     ,156,155,154
BEGIN DESCRIPTION:
Cross Section XS0.2 - K152-00-00-S01_CULVERT - DS - XS1
END DESCRIPTION:
XS GIS Cut Line= 3
      3008193.78       13912296.      3007003.95     13912114.11
      3006784.24     13912117.49
#Sta/Elev= 30
  3678.7   149.5  3798.7   148.4  3858.7   149.4  3968.7   150.2  4118.7   149.1
  4168.7   148.1  4378.7   147.4  4428.8   146.5  4448.7   146.3  4478.7   147.4
  4498.7   146.9  4528.7   147.1  4548.7   146.5  4618.7     147  4708.7   146.2
  4768.7   146.5  4882.4   146.1  4902.4   145.5  4912.4   144.7  4978.6  143.68
  4990.1  140.34  4999.4  138.94  5004.6  139.41  5005.6  140.34  5007.2  142.79
  5052.4   143.7  5062.4   145.2  5082.4   149.6  5092.4   150.6  5102.2   150.8
#Mann= 5 ,-1 , 0
  3678.7     .06       0  4428.8     .09       0  4978.6     .07       0
  5007.2     .06       0  5102.2      .2       0
Bank Sta=4978.6,5007.2
Exp/Cntr=0.3,0.1

Type RM Length L Ch R = 1 ,530     ,0,0,0
BEGIN DESCRIPTION:
Cross Section XS0.1
END DESCRIPTION:
XS GIS Cut Line= 3
       3008210.6       13912262.      3006997.19     13911965.38
      3006726.78     13911958.62
#Sta/Elev= 30
  3652.7   148.6  3722.7   149.3  3912.7   148.6  3972.7     149  4162.7   148.2
  4392.7   145.7  4469.8  145.67  4502.7   145.6  4532.7   146.3  4612.7   145.8
  4642.7   146.5  4702.7   146.7  4742.7   145.5  4852.7   146.7  4902.1   144.2
  4978.6  142.16  4990.1  138.82  4999.4  137.42  5004.6  137.89  5005.6  138.82
  5007.2  141.27  5010.8  143.06  5032.1   145.2  5082.1   146.1  5092.1   147.3
  5102.1     148  5112.1   149.5  5142.1   150.3  5152.1     150  5172.6   150.1
#Mann= 5 ,-1 , 0
  3652.7     .06       0  4469.8     .09       0  4978.6     .07       0
  5010.8     .06       0  5172.6      .2       0
Bank Sta=4978.6,5010.8
Exp/Cntr=0.3,0.1

Chan Stop Cuts=-1
Use User Specified Reach Order=0
User Specified Reach Order=K152-00-00      ,K152-00-00_0005